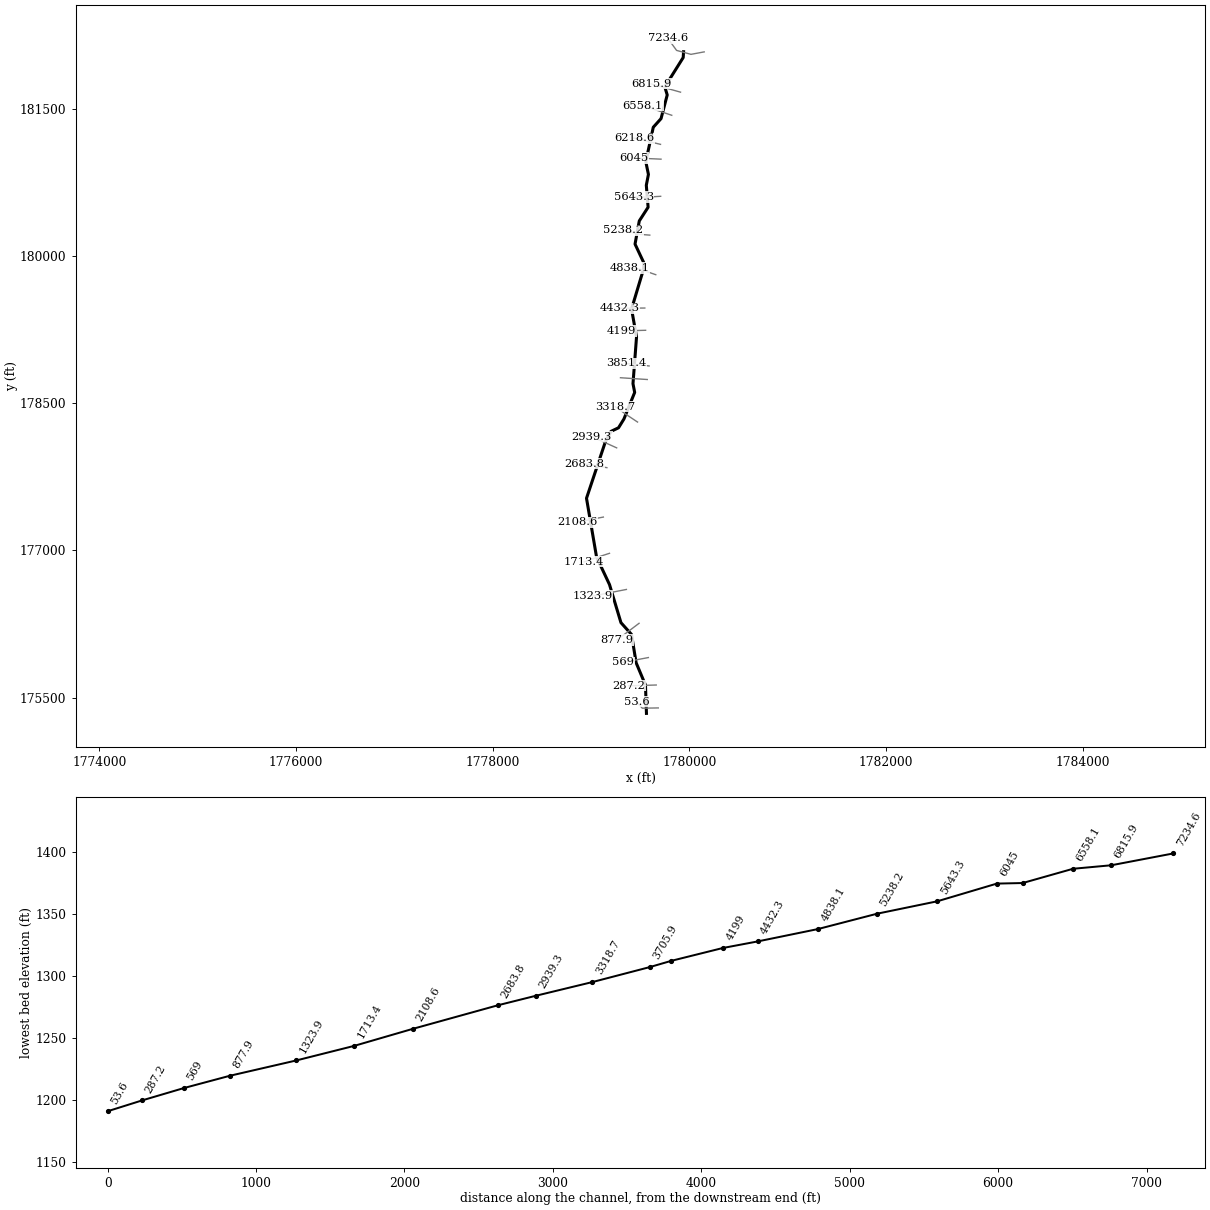
--- Left Fork Davy Branch.prj (project) ---

Proj Title=Left Fork Davy Branch
Current Plan=p01
Default Exp/Contr=0,0
English Units
Geom File=g01
Flow File=f01
Plan File=p01
BEGIN DESCRIPTION:
END DESCRIPTION:
DSS Export Rating Curves= 0
DSS Export Rating Curve Sorted= 0
DSS Export Volume Flow Curves= 0
DXF OffsetX= 0
DXF OffsetY= 0
DXF ScaleX= 0
DXF ScaleY= 0

--- Left Fork Davy Branch.p01 (plan) ---

Plan Title=Floodplain
Program Version=4.00
Geom File=g01
Flow File=f01
K Sum by GR=0
Std Step Tol=0.01
Critical Tol=0.01
Num of Std Step Trials=20
Max Error Tol=0.3
Flow Tol Ratio=0.001
Split Flow NTrial=30
Split Flow Tol=0.02
Split Flow Ratio=0.02
Log Output Level=0
Friction Slope Method=1
Unsteady Friction Slope Method=2
Unsteady Bridges Friction Slope Method=1
Global Log Level=0
CheckData=False
Run HTab=0
Run UNet=0
Run PostProcess=0
UNET Theta=0
UNET Theta Warmup=0
UNET ZTol=0
UNET ZSATol=0
UNET MxIter=0
UNET MaxInSteps=0
UNET DtIC=0
UNET DtMin=0
UNET MaxCRTS=0
UNET WFStab=0
UNET SFStab=0
UNET WFX=0
UNET SFX=0
UNET DSS MLevel=0
UNET DZMax Abort=0
UNET Convert EG Bridges=0
UNET Use Existing IB Tables=0
UNET Froude Limit=0
UNET Froude Power=0
Write IC File=0
Echo Input=False
Echo Output=False
Write Detailed=0

--- Left Fork Davy Branch.f01 (steady flow) ---

Flow Title=NFF Regression Equation
Program Version=4.00
Number of Profiles=1
Profile Names=P100yr
River Rch & RM=Left Fork Dav...,Main      ,7234.6
530.3343
River Rch & RM=Left Fork Dav...,Main      ,6815.9
530.9493
River Rch & RM=Left Fork Dav...,Main      ,6815.9
606.1956
River Rch & RM=Left Fork Dav...,Main      ,4432.3
673.5024
River Rch & RM=Left Fork Dav...,Main      ,2939.3
740.0548
River Rch & RM=Left Fork Dav...,Main      ,287.2
810.6349
Boundary for River Rch & Prof#=Left Fork Dav...,Main      ,1
Up Type=0
Dn Type=3
Dn Slope=0.03501

--- Left Fork Davy Branch.g01 (geometry) ---

Geom Title=Geometry
Program Version=4.00

River Reach=Left Fork Dav...,Main
Reach XY= 30
     1779942.043      182081.428     1779938.161      182021.907
     1779751.138      181722.666     1779775.719      181640.917
     1779712.835      181399.673     1779633.945      181311.635
     1779557.738      180960.656     1779584.584      180830.912
     1779563.058      180720.529     1779581.352      180496.434
     1779491.599      180356.947     1779448.349      180120.885
      1779539.62      179926.479     1779536.189      179870.456
     1779413.008      179459.501     1779463.588      179174.162
     1779427.572      178697.961     1779444.723      178609.352
     1779335.533      178338.381     1779280.402       178248.74
     1779204.327      178212.466     1779146.311      178105.139
     1778954.801      177530.611     1779056.972      176932.045
     1779188.693      176650.966     1779305.235      176262.648
      1779412.46      176142.826     1779459.586      175853.904
     1779554.483      175626.951       1779564.5      175338.228

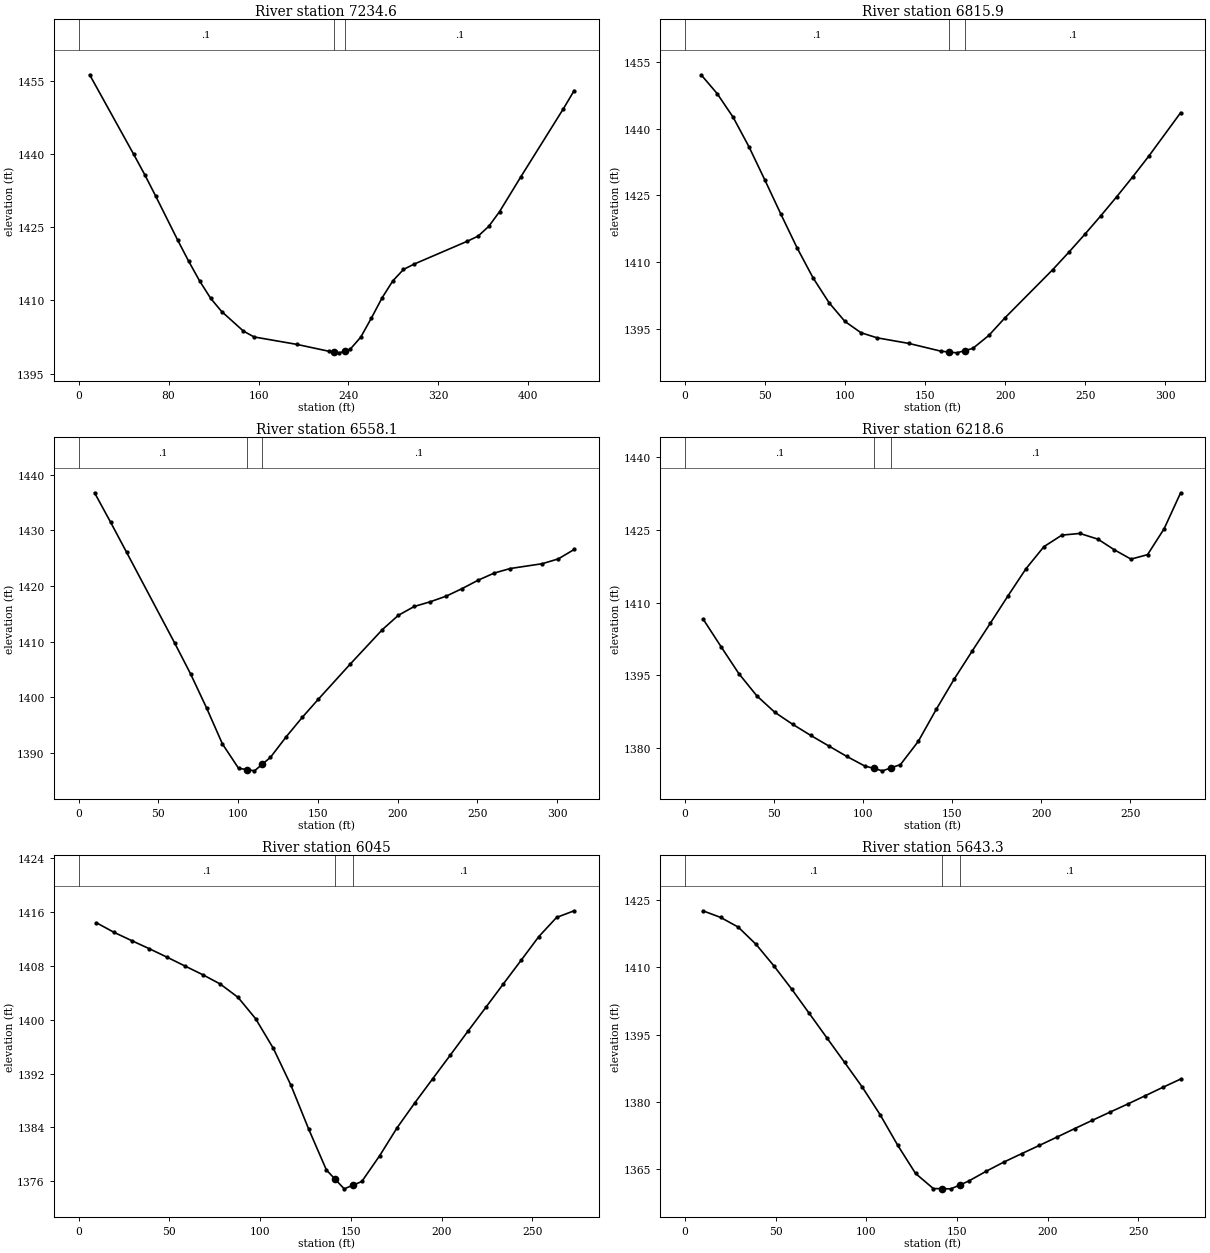
Type RM Length L Ch R = 1 ,7234.6  ,419.8,418.8,417.7
XS GIS Cut Line= 4
     1780151.805       182079.79     1780017.172      182054.546
     1779870.759      182094.936     1779781.565      182217.789
#Sta/Elev= 30
     9.8 1456.26    48.9 1439.98    58.7 1435.81    68.5  1431.4    88.1 1422.35
    97.8 1418.05   107.6 1413.98   117.4 1410.42   127.2 1407.71   146.5 1403.71
     156  1402.5   193.9 1400.98   222.4 1399.57   226.9 1399.41   231.9 1399.24
   236.9 1399.61   241.4 1399.95   250.9 1402.45   260.4 1406.39   269.9 1410.53
   279.4 1413.99   288.9 1416.34   298.3 1417.43   345.8 1422.14   355.3 1423.18
   364.8 1425.19   374.3 1428.18   393.2 1435.31   431.2 1449.33   440.7 1453.02
#Mann= 3 , 0 , 0
       0      .1       0   226.9    .045       0   236.9      .1       0
Bank Sta=226.9,236.9
XS Rating Curve= 0 ,0
Exp/Cntr=0.3,0.1

Type RM Length L Ch R = 1 ,6815.9  ,257.8,257.8,257.8
XS GIS Cut Line= 2
     1779911.149       181669.16     1779613.274      181753.306
#Sta/Elev= 28
      10  1452.1      20 1447.89      30 1442.57    39.9 1435.93    49.9 1428.41
    59.9 1420.75    69.9 1413.27    79.9 1406.52    89.9 1400.93    99.8 1396.73
   109.8  1394.2   119.8 1393.05   139.8 1391.78   159.8 1390.04   164.7 1389.86
   169.7 1389.67   174.7 1390.17   179.7 1390.66   189.7 1393.58   199.7  1397.5
   229.7 1408.38   239.6 1412.23   249.6 1416.26   259.6 1420.42   269.6 1424.73
   279.6  1429.2   289.6 1433.83   309.5 1443.59
#Mann= 3 , 0 , 0
       0      .1       0   164.7    .045       0   174.7      .1       0
Bank Sta=164.7,174.7
XS Rating Curve= 0 ,0
Exp/Cntr=0.3,0.1

Type RM Length L Ch R = 1 ,6558.1  ,337.8,339.5,341.3
XS GIS Cut Line= 2
     1779821.955      181433.553     1779527.446      181532.845
#Sta/Elev= 28
      10 1436.73    20.1 1431.42    30.1 1426.04    60.2 1409.79    70.2 1404.24
    80.2 1398.15    90.2 1391.66   100.3  1387.3   105.3 1387.07   110.3 1386.84
   115.3 1388.05   120.3 1389.26   130.3 1392.99   140.4 1396.48   150.4 1399.71
   170.4 1406.01   190.5 1412.18   200.5 1414.74   210.5 1416.33   220.6 1417.18
   230.6 1418.19   240.6 1419.55   250.6 1421.05   260.7 1422.33   270.7 1423.14
   290.7    1424   300.8 1424.86   310.8 1426.56
#Mann= 3 , 0 , 0
       0      .1       0   105.3    .045       0   115.3      .1       0
Bank Sta=105.3,115.3
XS Rating Curve= 0 ,0
Exp/Cntr=0.3,0.1

Type RM Length L Ch R = 1 ,6218.6  ,169.8,173.6,177.4
XS GIS Cut Line= 3
     1779707.517      181137.361     1779482.007      181191.214
     1779436.569      181201.312
#Sta/Elev= 30
    10.1 1406.61    20.2 1400.91    30.2 1395.36    40.3 1390.78    50.4 1387.39
    60.5  1384.9    70.6 1382.63    80.6 1380.48    90.7 1378.33   100.8 1376.35
   105.9 1375.84   110.9 1375.33   115.9 1375.97     121 1376.62     131  1381.4
   141.1    1388   151.2 1394.25   161.3 1400.02   171.4  1405.7   181.4 1411.38
   191.5 1416.97   201.6 1421.52   211.7  1423.9   221.8 1424.24   231.9 1423.07
   241.2 1420.86   250.5 1418.95   259.8 1419.87   269.1 1425.19   278.4 1432.62
#Mann= 3 , 0 , 0
       0      .1       0   105.9    .045       0   115.9      .1       0
Bank Sta=105.9,115.9
XS Rating Curve= 0 ,0
Exp/Cntr=0.3,0.1

Type RM Length L Ch R = 1 ,6045    ,400.3,401.7,402.4
XS GIS Cut Line= 3
     1779712.903      180986.442     1779576.544      180992.639
     1779440.185      180998.837
#Sta/Elev= 30
     9.8 1414.38    19.5 1412.96    29.3 1411.72      39 1410.52    48.8 1409.26
    58.5 1407.97    68.3 1406.68      78 1405.29    87.8 1403.31    97.5 1400.14
   107.3 1395.72     117 1390.23   126.8 1383.71   136.5 1377.68   141.2 1376.34
   146.3 1374.88   151.2 1375.43     156 1375.97   165.8 1379.78   175.5 1383.97
   185.3 1387.68     195  1391.2   204.8 1394.75   214.5 1398.29   224.3 1401.81
     234 1405.31   243.8 1408.82   253.5 1412.32   263.3 1415.17     273 1416.16
#Mann= 3 , 0 , 0
       0      .1       0   141.2    .045       0   151.2      .1       0
Bank Sta=141.2,151.2
XS Rating Curve= 0 ,0
Exp/Cntr=0.3,0.1

Type RM Length L Ch R = 1 ,5643.3  ,410.6,405.1,400.4
XS GIS Cut Line= 3
     1779709.217      180607.922     1779572.585       180599.97
     1779436.153      180601.055
#Sta/Elev= 30
     9.8  1422.6    19.6 1421.12    29.3 1418.96    39.1 1415.13    48.9 1410.35
    58.7 1405.18    68.4 1399.76    78.2 1394.26      88 1388.77    97.8 1383.23
   107.5 1377.16   117.3 1370.28   127.1 1364.02   136.9 1360.65   141.6 1360.62
   146.6 1360.59   151.6 1361.47   156.4 1362.32   166.1 1364.52   175.8 1366.56
   185.6 1368.43   195.3 1370.26   205.1 1372.13   214.8 1374.01   224.6 1375.87
   234.3 1377.69   244.1  1379.5   253.8 1381.36   263.6 1383.25   273.3 1385.07
#Mann= 3 , 0 , 0
       0      .1       0   141.6    .045       0   151.6      .1       0
Bank Sta=141.6,151.6
XS Rating Curve= 0 ,0
Exp/Cntr=0.3,0.1

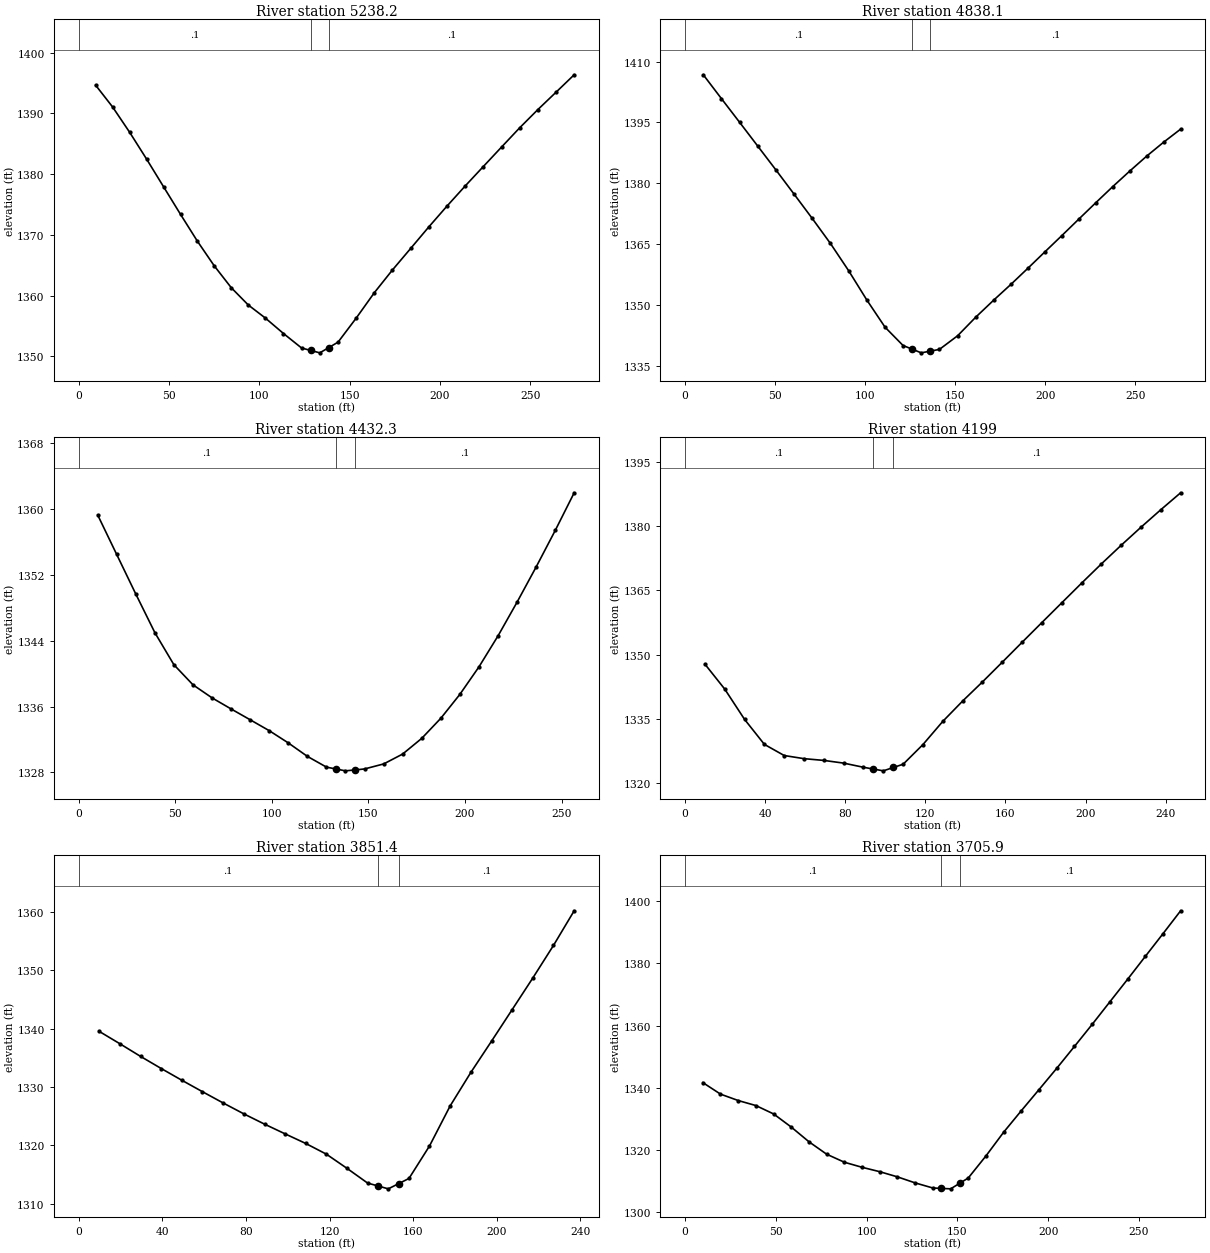
Type RM Length L Ch R = 1 ,5238.2  ,402.2,400,397.8
XS GIS Cut Line= 3
     1779598.484      180212.242     1779495.471      180220.176
     1779329.481      180261.245
#Sta/Elev= 30
     9.4 1394.65    18.8 1391.06    28.2 1386.91    37.6 1382.49      47 1377.93
    56.4 1373.38    65.7 1368.98    75.1 1364.89    84.5  1361.3    93.9 1358.46
   103.3 1356.32   113.4 1353.76   123.4 1351.38   128.5 1350.97   133.5 1350.58
   138.5 1351.45   143.6 1352.34   153.6 1356.28   163.7 1360.49   173.7 1364.22
   183.8 1367.77   193.8  1371.3   203.9 1374.74     214 1378.06     224 1381.25
   234.1 1384.46   244.1 1387.62   254.2 1390.63   264.3  1393.5   274.3 1396.36
#Mann= 3 , 0 , 0
       0      .1       0   128.5    .045       0   138.5      .1       0
Bank Sta=128.5,138.5
XS Rating Curve= 0 ,0
Exp/Cntr=0.3,0.1

Type RM Length L Ch R = 1 ,4838.1  ,398.9,405.9,412.8
XS GIS Cut Line= 3
     1779659.186      179808.984     1779497.154      179865.082
     1779394.301      179877.913
#Sta/Elev= 30
    10.1 1406.77    20.2 1400.87    30.3 1395.02    40.3 1389.19    50.4  1383.3
    60.5 1377.32    70.6 1371.31    80.7 1365.14    90.8 1358.42   100.9 1351.19
     111 1344.49     121 1339.97   126.1 1339.06   131.1 1338.16   136.1 1338.58
   141.2 1339.01   151.3 1342.38   161.4 1346.98   171.5 1351.24   180.9 1355.06
   190.3 1359.03   199.7 1363.06   209.2 1367.11   218.6 1371.17     228  1375.2
   237.4 1379.17   246.9 1383.03   256.3 1386.72   265.7 1390.15   275.1 1393.36
#Mann= 3 , 0 , 0
       0      .1       0   126.1    .045       0   136.1      .1       0
Bank Sta=126.1,136.1
XS Rating Curve= 0 ,0
Exp/Cntr=0.3,0.1

Type RM Length L Ch R = 1 ,4432.3  ,233,233.3,233.6
XS GIS Cut Line= 2
     1779547.949      179469.289     1779291.449      179466.374
#Sta/Elev= 28
     9.9 1359.28    19.7  1354.5    29.6 1349.68    39.5 1344.97    49.3 1341.09
    59.2 1338.64    69.1 1337.05    78.9 1335.71    88.8 1334.39    98.7 1333.06
   108.5 1331.58   118.4 1329.94   128.3 1328.63   133.1 1328.41   138.1 1328.18
   143.1 1328.29     148 1328.41   157.9 1329.02   167.7 1330.22   177.6 1332.13
   187.5 1334.58   197.3 1337.47   207.2 1340.82   217.1  1344.6   226.9 1348.68
   236.8 1352.97   246.7 1357.42   256.5    1362
#Mann= 3 , 0 , 0
       0      .1       0   133.1    .045       0   143.1      .1       0
Bank Sta=133.1,143.1
XS Rating Curve= 0 ,0
Exp/Cntr=0.3,0.1

Type RM Length L Ch R = 1 ,4199    ,350.3,347.6,344.8
XS GIS Cut Line= 2
     1779556.055      179242.406     1779308.668      179235.675
#Sta/Elev= 27
     9.9 1347.79    19.8 1341.97    29.7 1334.91    39.6 1329.08    49.5 1326.48
    59.4 1325.75    69.3 1325.34    79.2 1324.71    89.1 1323.74      94 1323.33
      99 1322.91     104 1323.69   108.9 1324.45   118.8 1329.04   128.7 1334.44
   138.6 1339.18   148.5 1343.64   158.4 1348.24   168.3 1352.88   178.2 1357.49
   188.1 1362.08     198 1366.66   207.9 1371.16   217.8 1375.51   227.7 1379.72
   237.6  1383.8   247.5 1387.75
#Mann= 3 , 0 , 0
       0      .1       0      94    .045       0     104      .1       0
Bank Sta=94,104
XS Rating Curve= 0 ,0
Exp/Cntr=0.3,0.1

Type RM Length L Ch R = 1 ,3851.4  ,144.7,145.5,146.3
XS GIS Cut Line= 2
     1779591.396      178878.898     1779355.789      178904.142
#Sta/Elev= 26
     9.9 1339.51    19.7 1337.41    29.6 1335.24    39.5 1333.16    49.4 1331.14
    59.2 1329.19    69.1 1327.26      79 1325.39    88.9 1323.63    98.7 1321.97
   108.6 1320.32   118.5 1318.48   128.4 1316.04   138.2 1313.53   143.1 1313.04
   148.1 1312.54   153.1 1313.44     158 1314.32   167.8 1319.88   177.7 1326.76
   187.6  1332.5   197.5 1337.86   207.3 1343.23   217.2 1348.66   227.1 1354.25
     237 1360.19
#Mann= 3 , 0 , 0
       0      .1       0   143.1    .045       0   153.1      .1       0
Bank Sta=143.1,153.1
XS Rating Curve= 0 ,0
Exp/Cntr=0.3,0.1

Type RM Length L Ch R = 1 ,3705.9  ,397.8,387.2,375.9
XS GIS Cut Line= 3
     1779572.753      178740.728     1779436.555      178749.807
     1779300.357      178758.887
#Sta/Elev= 30
     9.8 1341.66    19.5 1337.96    29.3 1335.89      39 1334.28    48.8 1331.57
    58.5 1327.35    68.3  1322.6      78 1318.62    87.8 1316.03    97.5 1314.41
   107.3 1312.99     117 1311.33   126.8 1309.38   136.5 1307.75   141.2 1307.62
   146.3 1307.48   151.2 1309.24     156 1310.97   165.8 1318.11   175.5 1325.71
   185.3 1332.67     195 1339.43   204.8 1346.31   214.5 1353.31   224.3 1360.43
     234 1367.65   243.8 1374.93   253.5 1382.25   263.3  1389.6     273 1396.96
#Mann= 3 , 0 , 0
       0      .1       0   141.2    .045       0   151.2      .1       0
Bank Sta=141.2,151.2
XS Rating Curve= 0 ,0
Exp/Cntr=0.3,0.1

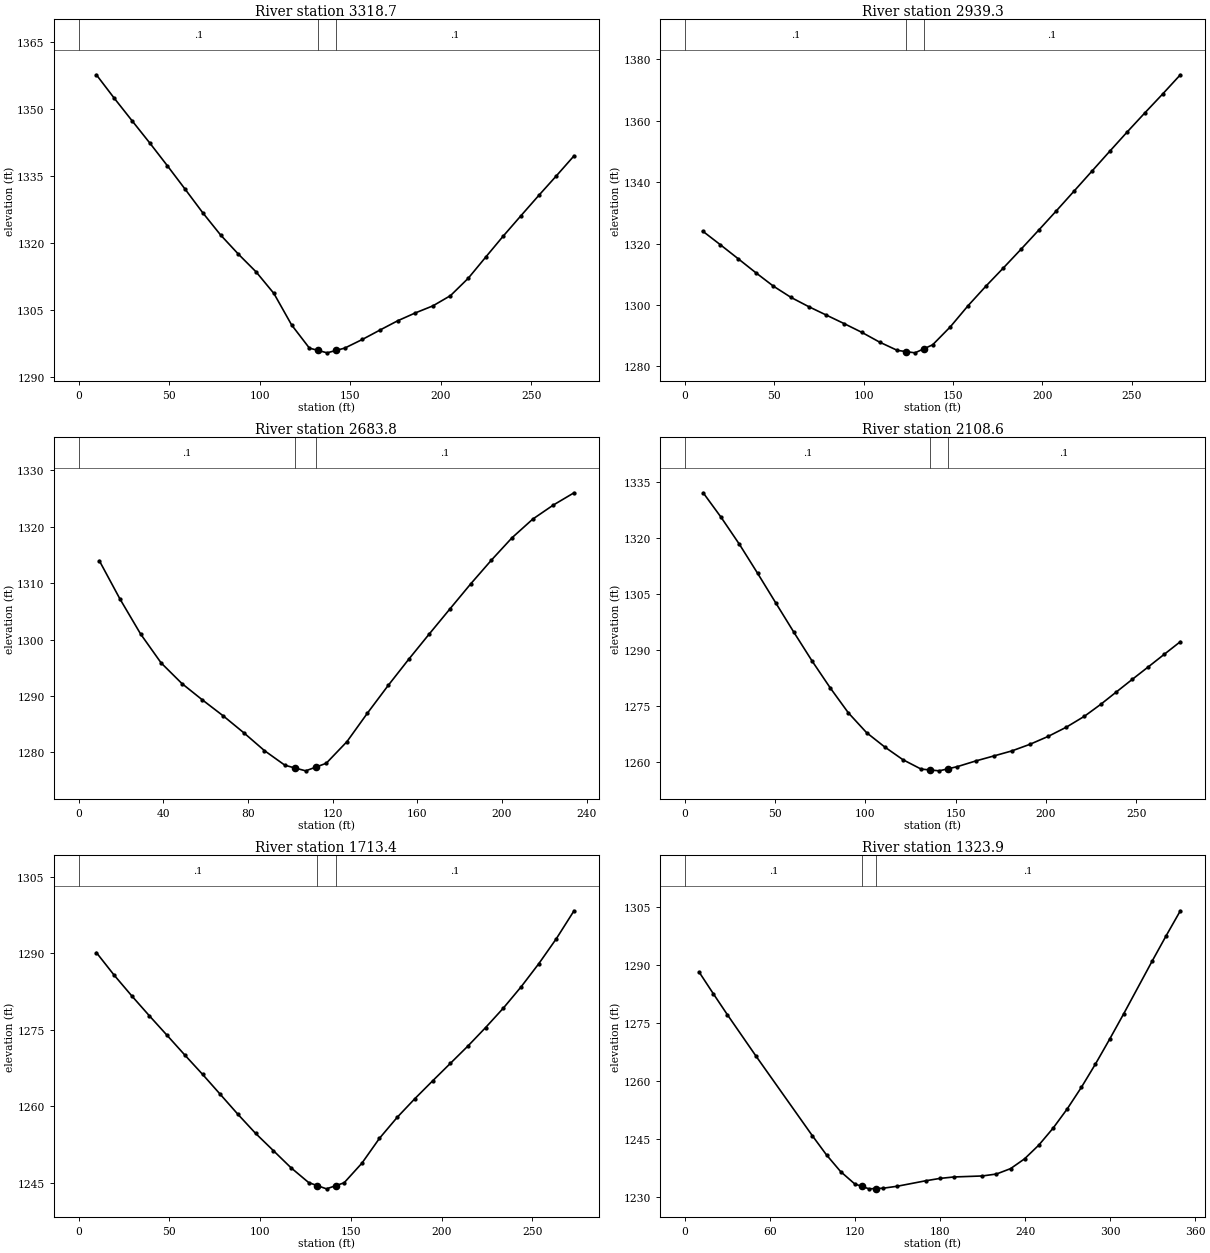
Type RM Length L Ch R = 1 ,3318.7  ,377,379.4,382.3
XS GIS Cut Line= 3
     1779473.969      178307.245     1779359.777      178383.262
     1779248.977       178462.66
#Sta/Elev= 30
     9.8 1357.64    19.6 1352.43    29.4  1347.4    39.2 1342.41      49 1337.27
    58.8 1332.02    68.6 1326.71    78.4 1321.76    88.2 1317.48      98  1313.5
   107.8 1308.68   117.6 1301.62   127.4 1296.44   132.2 1295.92   137.2 1295.38
   142.2 1295.93   146.9 1296.44   156.7 1298.39   166.4 1300.49   176.1 1302.55
   185.9 1304.32   195.6  1305.9   205.3 1308.19   215.1 1312.08   224.8 1316.84
   234.5 1321.56   244.3 1326.13     254 1330.61   263.8 1335.03   273.5 1339.49
#Mann= 3 , 0 , 0
       0      .1       0   132.2    .045       0   142.2      .1       0
Bank Sta=132.2,142.2
XS Rating Curve= 0 ,0
Exp/Cntr=0.3,0.1

Type RM Length L Ch R = 1 ,2939.3  ,250.3,255.5,260.7
XS GIS Cut Line= 2
     1779261.546      178044.175      1779009.11      178158.613
#Sta/Elev= 30
     9.9 1324.05    19.8 1319.61    29.7 1315.08    39.6 1310.51    49.5  1306.1
    59.4 1302.42    69.3 1299.41    79.2 1296.65    89.1 1293.89      99 1291.04
   108.9 1287.87   118.8 1285.18   123.7 1284.78   128.7 1284.37   133.7 1285.69
   138.6 1286.99   148.5 1292.85   158.4 1299.72   168.3 1306.04   178.2 1312.05
   188.1 1318.16     198 1324.39   207.9  1330.7   217.8 1337.12   227.7 1343.56
   237.6    1350   247.5 1356.38   257.4 1362.61   267.3 1368.72   277.2 1374.99
#Mann= 3 , 0 , 0
       0      .1       0   123.7    .045       0   133.7      .1       0
Bank Sta=123.7,133.7
XS Rating Curve= 0 ,0
Exp/Cntr=0.3,0.1

Type RM Length L Ch R = 1 ,2683.8  ,568,575.2,582.4
XS GIS Cut Line= 2
     1779162.255      177842.226     1778931.696      177882.616
#Sta/Elev= 26
     9.8 1313.98    19.5 1307.22    29.3 1300.98      39 1295.85    48.8  1292.2
    58.5 1289.29    68.3 1286.47      78 1283.48    87.8  1280.3    97.5  1277.7
   102.3 1277.21   107.3 1276.71   112.3  1277.4     117 1278.05   126.8 1281.89
   136.5 1286.96   146.3 1291.87     156 1296.51   165.8 1301.04   175.6  1305.5
   185.3 1309.89   195.1 1314.11   204.8 1318.06   214.6 1321.37   224.3 1323.86
   234.1 1326.04
#Mann= 3 , 0 , 0
       0      .1       0   102.3    .045       0   112.3      .1       0
Bank Sta=102.3,112.3
XS Rating Curve= 0 ,0
Exp/Cntr=0.3,0.1

Type RM Length L Ch R = 1 ,2108.6  ,392.6,395.1,398.2
XS GIS Cut Line= 3
     1779126.193       177338.87     1778908.767      177297.595
     1778856.934      177286.294
#Sta/Elev= 30
    10.1 1332.22    20.1 1325.59    30.2 1318.38    40.2 1310.66    50.3 1302.68
    60.4 1294.75    70.4 1287.11    80.5 1279.86    90.5 1273.19   100.6 1267.87
   110.7 1264.01   120.7 1260.62   130.8 1258.09   135.8 1257.86   140.8 1257.62
   145.8 1258.18   150.9 1258.75     161 1260.26     171  1261.6   181.1 1262.97
   191.1 1264.74   201.2 1266.86   211.2 1269.32   221.3 1272.27   230.2 1275.42
     239  1278.8   247.8 1282.17   256.7 1285.53   265.5 1288.89   274.4 1292.27
#Mann= 3 , 0 , 0
       0      .1       0   135.8    .045       0   145.8      .1       0
Bank Sta=135.8,145.8
XS Rating Curve= 0 ,0
Exp/Cntr=0.3,0.1

Type RM Length L Ch R = 1 ,1713.4  ,391.9,389.5,386.6
XS GIS Cut Line= 3
     1779188.499      176969.571     1779058.606      176927.429
      1778929.94      176881.881
#Sta/Elev= 30
     9.8 1290.13    19.5 1285.75    29.3 1281.65      39 1277.75    48.8 1273.91
    58.5 1270.08    68.3 1266.29      78  1262.4    87.8 1258.46    97.5 1254.74
   107.3 1251.36     117 1248.01   126.8 1245.09   131.6 1244.49   136.6 1243.87
   141.6 1244.48   146.3 1245.05   156.1 1248.89   165.8 1253.77   175.6 1257.89
   185.3 1261.53   195.1 1265.02   204.8 1268.42   214.6 1271.86   224.3 1275.46
   234.1 1279.28   243.8 1283.41   253.5 1287.92   263.3 1292.88     273 1298.32
#Mann= 3 , 0 , 0
       0      .1       0   131.6    .045       0   141.6      .1       0
Bank Sta=131.6,141.6
XS Rating Curve= 0 ,0
Exp/Cntr=0.3,0.1

Type RM Length L Ch R = 1 ,1323.9  ,436.8,446.1,455.3
XS GIS Cut Line= 2
      1779360.54       176601.25     1779017.499      176533.743
#Sta/Elev= 30
      10 1288.21      20 1282.62      30 1277.15    49.9  1266.6    89.9 1245.88
    99.9 1240.91   109.9 1236.58   119.9 1233.38   124.9 1232.76   129.9 1232.13
   134.9 1232.21   139.8 1232.29   149.8  1232.8   169.8 1234.21   179.8 1234.82
   189.8  1235.2   209.8 1235.46   219.8 1235.96   229.8 1237.36   239.7  1239.9
   249.7 1243.44   259.7 1247.78   269.7 1252.77   279.7 1258.35   289.7 1264.42
   299.7 1270.84   309.7 1277.46   329.6 1290.97   339.6 1297.61   349.6 1304.06
#Mann= 3 , 0 , 0
       0      .1       0   124.9    .045       0   134.9      .1       0
Bank Sta=124.9,134.9
XS Rating Curve= 0 ,0
Exp/Cntr=0.3,0.1

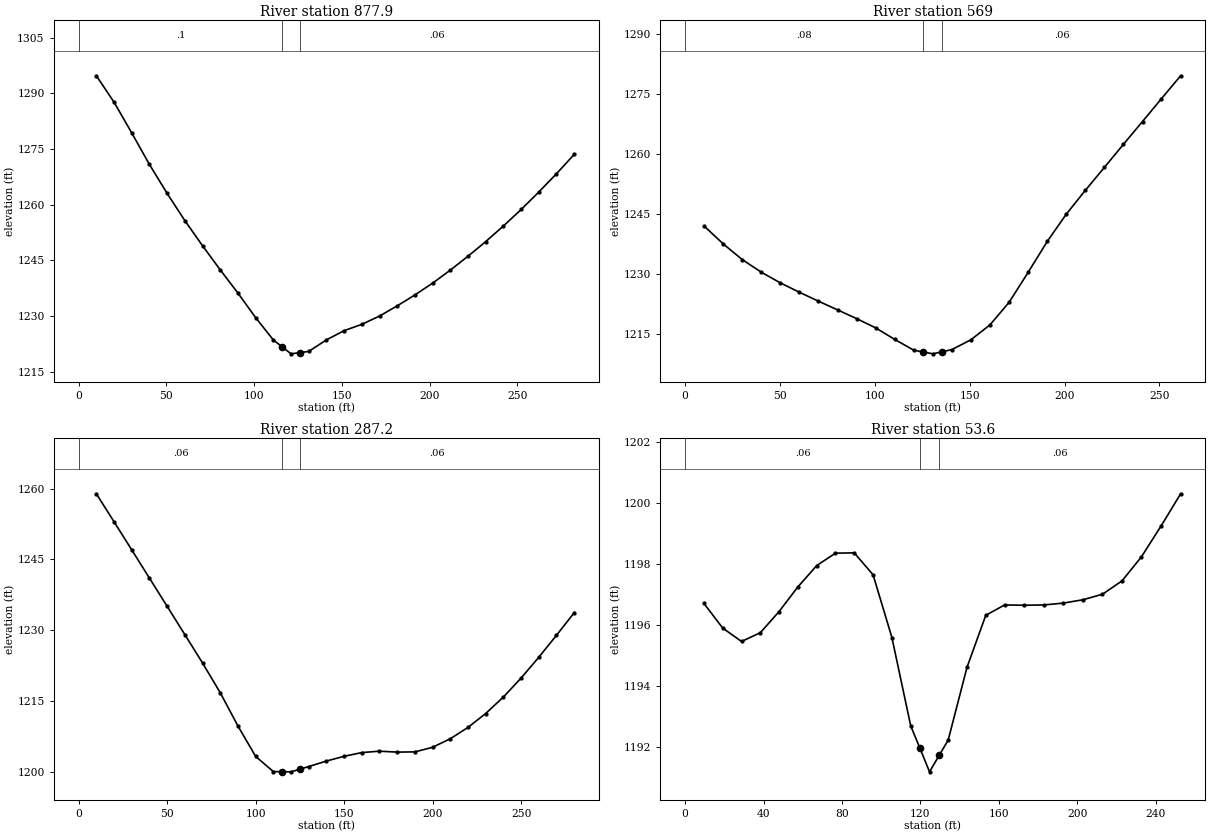
Type RM Length L Ch R = 1 ,877.9   ,318.2,308.9,299.6
XS GIS Cut Line= 2
      1779489.37      176256.296     1779264.281      176085.901
#Sta/Elev= 30
    10.1 1294.74    20.2 1287.61    30.2 1279.39    40.3 1270.87    50.4 1263.06
    60.5 1255.72    70.6 1248.93    80.7 1242.42    90.7 1236.22   100.8 1229.59
   110.9 1223.56     116 1221.67     121 1219.81     126 1220.13   131.1 1220.47
   141.2 1223.58   151.2 1226.05   161.3 1227.75   171.4 1229.99   181.5 1232.74
   191.6 1235.69   201.7 1238.87   211.7 1242.35   221.8 1246.11   231.9 1250.05
     242 1254.27   252.1 1258.71   262.1 1263.39   272.2 1268.33   282.3 1273.54
#Mann= 3 , 0 , 0
       0      .1       0     116    .045       0     126     .06       0
Bank Sta=116,126
XS Rating Curve= 0 ,0
Exp/Cntr=0.3,0.1

Type RM Length L Ch R = 1 ,569     ,284.8,281.7,278.6
XS GIS Cut Line= 2
     1779584.034      175907.092      1779327.39      175858.708
#Sta/Elev= 28
      10  1241.9    20.1 1237.43    30.1 1233.51    40.2 1230.34    50.2 1227.68
    60.3 1225.32    70.3  1223.1    80.4 1220.92    90.4 1218.74   100.4 1216.44
   110.5 1213.53   120.5 1210.85   125.6 1210.39   130.6 1209.93   135.6 1210.46
   140.6 1210.99   150.7 1213.46   160.7 1217.18   170.8 1222.83   180.8  1230.3
   190.9 1238.05   200.9 1244.85   210.9 1250.79     221 1256.56     231 1262.31
   241.1 1268.04   251.1 1273.76   261.2 1279.48
#Mann= 3 , 0 , 0
       0     .08       0   125.6    .045       0   135.6     .06       0
Bank Sta=125.6,135.6
XS Rating Curve= 0 ,0
Exp/Cntr=0.3,0.1

Type RM Length L Ch R = 1 ,287.2   ,233.9,233.6,233.4
XS GIS Cut Line= 2
     1779663.972      175627.308     1779384.188      175618.894
#Sta/Elev= 30
      10  1258.9      20 1252.97      30 1247.01      40 1241.02      50 1235.04
      60 1229.04      70 1223.03      80 1216.72      90 1209.67     100 1203.22
     110 1200.01     115 1199.98     120 1199.96     125 1200.52     130 1201.09
     140 1202.25     150 1203.26   159.9 1204.04   169.9 1204.34   179.9 1204.14
   189.9 1204.19   199.9 1205.16   209.9 1206.97   219.9 1209.37   229.9 1212.32
   239.9 1215.81   249.9 1219.83   259.9 1224.24   269.9  1228.9   279.9 1233.68
#Mann= 3 , 0 , 0
       0     .06       0     115    .045       0     125     .06       0
Bank Sta=115,125
XS Rating Curve= 0 ,0
Exp/Cntr=0.3,0.1

Type RM Length L Ch R = 1 ,53.6    ,52.3,53.6,54.8
XS GIS Cut Line= 3
     1779685.008      175393.805     1779522.027       175390.97
     1779461.989      175457.707
#Sta/Elev= 28
     9.6  1196.7    19.2 1195.89    28.8 1195.45    38.4 1195.74    47.9 1196.43
    57.5 1197.24    67.1 1197.94    76.7 1198.35    86.3 1198.36    95.9 1197.64
   105.5 1195.58   115.1 1192.68   119.7 1191.96   124.7 1191.17   129.7 1191.72
   134.2 1192.21   143.8  1194.6   153.4 1196.31     163 1196.65     173 1196.64
     183 1196.65   192.9 1196.71   202.9 1196.82   212.9    1197   222.9 1197.44
   232.8 1198.23   242.8 1199.24   252.8  1200.3
#Mann= 3 , 0 , 0
       0     .06       0   119.7    .045       0   129.7     .06       0
Bank Sta=119.7,129.7
XS Rating Curve= 0 ,0
Exp/Cntr=0.3,0.1

Chan Stop Cuts=-1
Use User Specified Reach Order=0